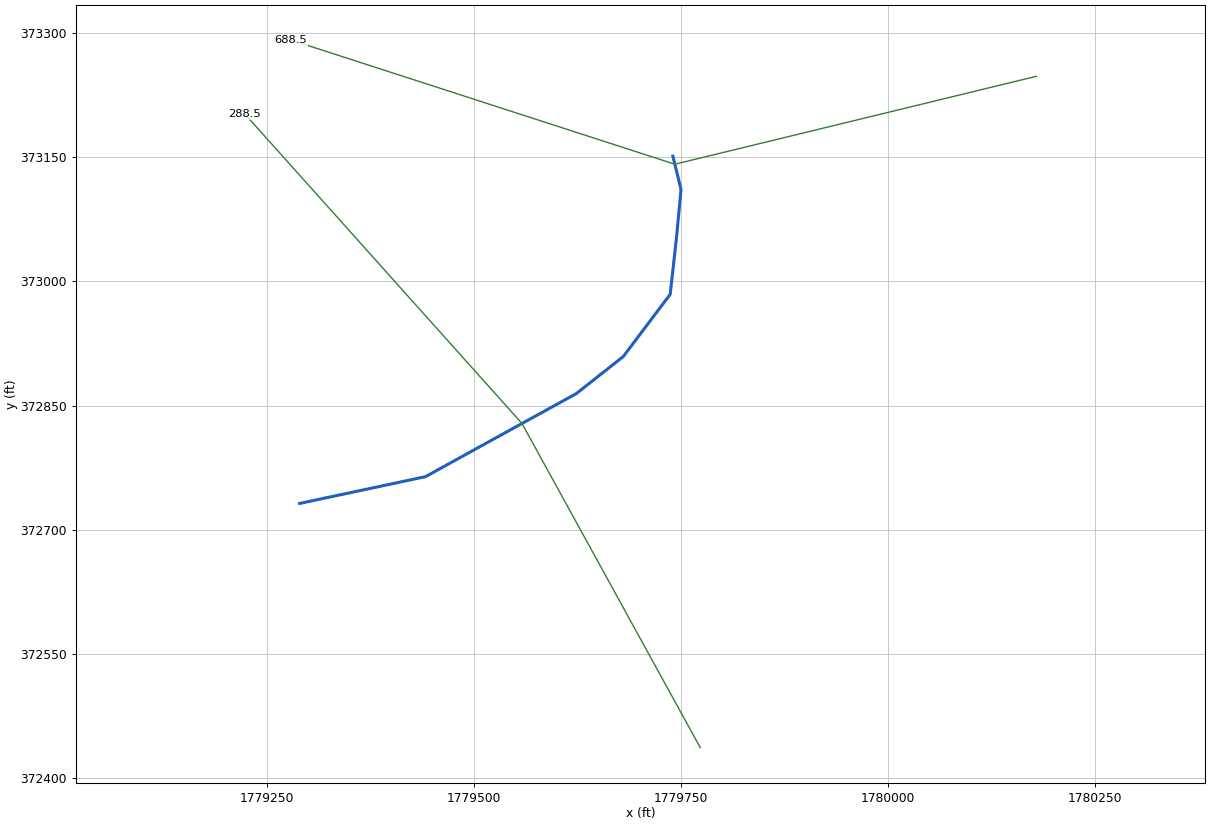
--- NP6.prj (project) ---

Proj Title=NP6
Current Plan=p01
Default Exp/Contr=0,0
English Units
Geom File=g01
Flow File=f01
Plan File=p01
BEGIN DESCRIPTION:
END DESCRIPTION:
DSS Export Rating Curves= 0
DSS Export Rating Curve Sorted= 0
DSS Export Volume Flow Curves= 0
DXF OffsetX= 0
DXF OffsetY= 0
DXF ScaleX= 0
DXF ScaleY= 0

--- NP6.p01 (plan) ---

Plan Title=Floodplain
Program Version=4.00
Geom File=g01
Flow File=f01
K Sum by GR=0
Std Step Tol=0.01
Critical Tol=0.01
Num of Std Step Trials=20
Max Error Tol=0.3
Flow Tol Ratio=0.001
Split Flow NTrial=30
Split Flow Tol=0.02
Split Flow Ratio=0.02
Log Output Level=0
Friction Slope Method=1
Unsteady Friction Slope Method=2
Unsteady Bridges Friction Slope Method=1
Global Log Level=0
CheckData=False
Run HTab=0
Run UNet=0
Run PostProcess=0
UNET Theta=0
UNET Theta Warmup=0
UNET ZTol=0
UNET ZSATol=0
UNET MxIter=0
UNET MaxInSteps=0
UNET DtIC=0
UNET DtMin=0
UNET MaxCRTS=0
UNET WFStab=0
UNET SFStab=0
UNET WFX=0
UNET SFX=0
UNET DSS MLevel=0
UNET DZMax Abort=0
UNET Convert EG Bridges=0
UNET Use Existing IB Tables=0
UNET Froude Limit=0
UNET Froude Power=0
Write IC File=0
Echo Input=False
Echo Output=False
Write Detailed=0

--- NP6.f01 (steady flow) ---

Flow Title=NFF Regression Equation
Program Version=4.00
Number of Profiles=1
Profile Names=P100yr
River Rch & RM=NP6,Main      ,688.5
     722
River Rch & RM=NP6,Main      ,288.5
726.2800
Boundary for River Rch & Prof#=NP6,Main      ,1
Up Type=0
Dn Type=3
Dn Slope=0.031246

--- NP6.g01 (geometry) ---

Geom Title=USGS 3m DEM
Program Version=4.00

River Reach=NP6     ,Main
Reach XY= 9
     1779740.305      373151.162     1779750.118      373110.817
     1779744.666      373053.025     1779737.033      372984.328
     1779680.332      372909.089     1779623.630      372864.382
     1779536.396      372816.404     1779441.530      372764.064
     1779289.425      372731.701

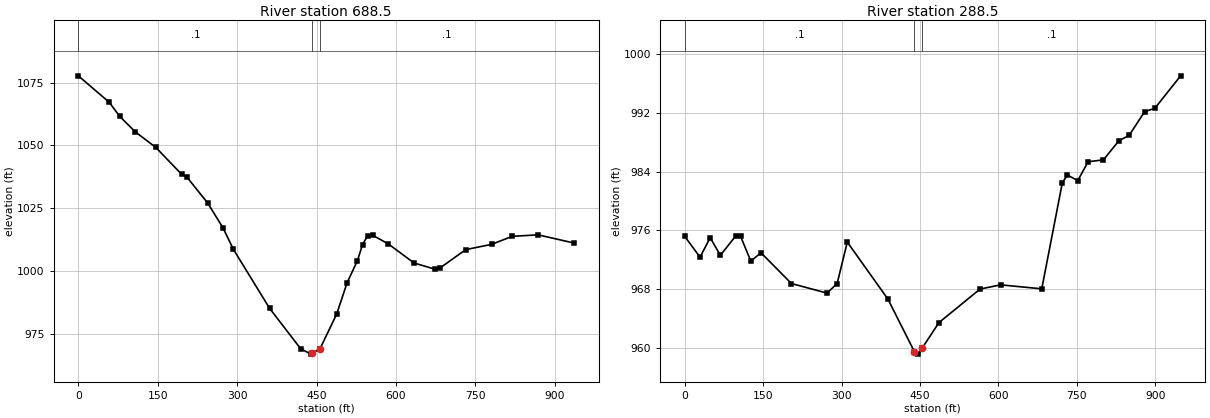
Type RM Length L Ch R = 1 ,688.5,429.804,400,389.248
XS GIS Cut Line= 3
     1780179.198      373247.627     1779742.668      373141.446
     1779278.815      373291.551
#Sta/Elev= 30
       0 1077.72    58.6 1067.14    78.1 1061.58   107.4 1055.44   146.5 1049.17
   195.3 1038.45   205.1 1037.39   244.2 1027.09   273.5 1017.09   293.0 1008.58
   361.4  985.08   420.0  969.00   439.5  966.84   441.8  967.13   456.8  969.05
   488.3  982.89   507.8  995.29   527.3 1004.06   537.0 1010.51   546.8 1014.07
   556.5 1014.16   585.8 1010.72   634.5 1003.13   673.5 1000.70   683.3 1001.16
   732.0 1008.48   780.8 1010.57   819.8 1013.77   868.5 1014.37   936.8 1011.09
#Mann= 3 , 0 , 0
       0     0.1       0   441.8   0.045       0   456.8     0.1       0
Bank Sta=   441.8,   456.8
Exp/Cntr=0.3,0.1

Type RM Length L Ch R = 1 ,288.5,295.169,288.523,276.67
XS GIS Cut Line= 3
     1779773.319      372436.817     1779558.009      372828.291
     1779223.395      373201.963
#Sta/Elev= 30
       0  975.16    29.1  972.34    48.6  974.99    68.0  972.59    97.1  975.21
   106.8  975.16   126.3  971.80   145.7  972.94   204.0  968.74   272.0  967.44
   291.4  968.74   310.8  974.40   388.5  966.62   439.3  959.43   446.8  959.11
   454.3  959.96   486.1  963.41   564.8  967.99   604.1  968.56   682.8  968.02
   722.2  982.52   732.0  983.53   751.7  982.79   771.3  985.35   800.8  985.62
   830.3  988.22   850.0  988.96   879.5  992.19   899.2  992.66   948.4  997.08
#Mann= 3 , 0 , 0
       0     0.1       0   439.3   0.045       0   454.3     0.1       0
Bank Sta=   439.3,   454.3
Exp/Cntr=0.3,0.1